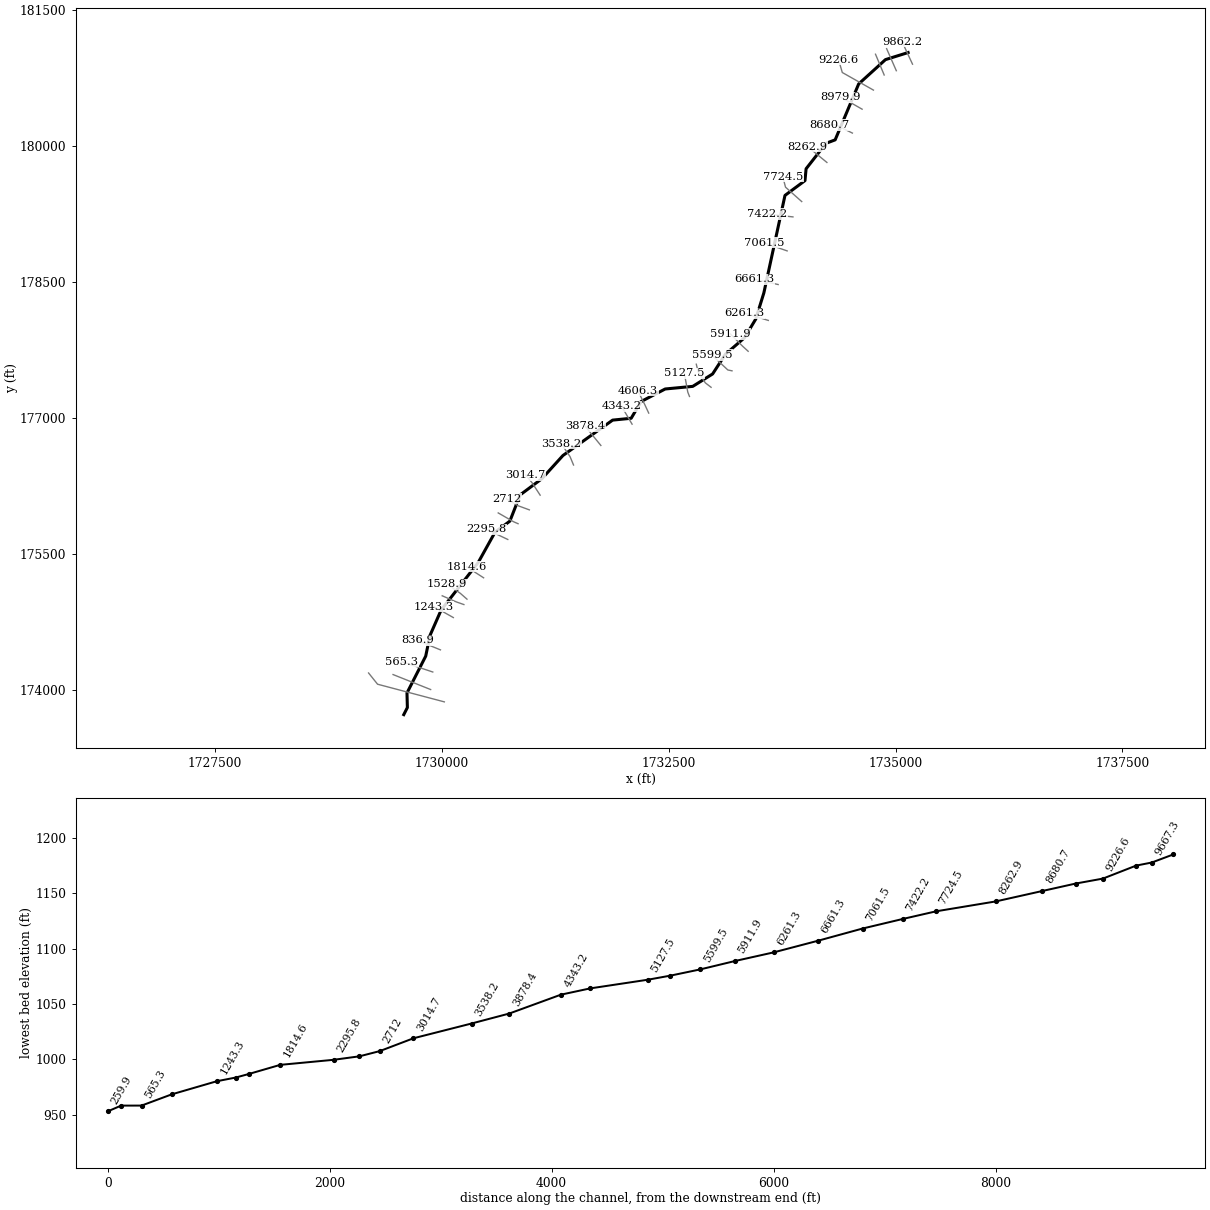
--- Johnnycake Branch.prj (project) ---

Proj Title=Johnnycake Branch
Current Plan=p01
Default Exp/Contr=0,0
English Units
Geom File=g01
Flow File=f01
Plan File=p01
BEGIN DESCRIPTION:
END DESCRIPTION:
DSS Export Rating Curves= 0
DSS Export Rating Curve Sorted= 0
DSS Export Volume Flow Curves= 0
DXF OffsetX= 0
DXF OffsetY= 0
DXF ScaleX= 0
DXF ScaleY= 0

--- Johnnycake Branch.p01 (plan) ---

Plan Title=Floodplain
Program Version=4.00
Geom File=g01
Flow File=f01
K Sum by GR=0
Std Step Tol=0.01
Critical Tol=0.01
Num of Std Step Trials=20
Max Error Tol=0.3
Flow Tol Ratio=0.001
Split Flow NTrial=30
Split Flow Tol=0.02
Split Flow Ratio=0.02
Log Output Level=0
Friction Slope Method=1
Unsteady Friction Slope Method=2
Unsteady Bridges Friction Slope Method=1
Global Log Level=0
CheckData=False
Run HTab=0
Run UNet=0
Run PostProcess=0
UNET Theta=0
UNET Theta Warmup=0
UNET ZTol=0
UNET ZSATol=0
UNET MxIter=0
UNET MaxInSteps=0
UNET DtIC=0
UNET DtMin=0
UNET MaxCRTS=0
UNET WFStab=0
UNET SFStab=0
UNET WFX=0
UNET SFX=0
UNET DSS MLevel=0
UNET DZMax Abort=0
UNET Convert EG Bridges=0
UNET Use Existing IB Tables=0
UNET Froude Limit=0
UNET Froude Power=0
Write IC File=0
Echo Input=False
Echo Output=False
Write Detailed=0

--- Johnnycake Branch.f01 (steady flow) ---

Flow Title=NFF Regression Equation
Program Version=4.00
Number of Profiles=1
Profile Names=P100yr
River Rch & RM=Johnnycake Br...,Main      ,9862.2
558.0507
River Rch & RM=Johnnycake Br...,Main      ,9526.6
566.5338
River Rch & RM=Johnnycake Br...,Main      ,9226.6
765.3689
River Rch & RM=Johnnycake Br...,Main      ,8262.9
788.0639
River Rch & RM=Johnnycake Br...,Main      ,7422.2
869.7525
River Rch & RM=Johnnycake Br...,Main      ,5911.9
924.1080
River Rch & RM=Johnnycake Br...,Main      ,3878.4
995.1004
River Rch & RM=Johnnycake Br...,Main      ,259.9
1103.772
Boundary for River Rch & Prof#=Johnnycake Br...,Main      ,1
Up Type=0
Dn Type=3
Dn Slope=0.025991

--- Johnnycake Branch.g01 (geometry) ---

Geom Title=Geometry
Program Version=4.00

River Reach=Johnnycake Br...,Main
Reach XY= 30
     1735137.962      181026.647     1734888.357      180948.571
     1734593.199      180680.719     1734333.941      180064.569
     1734233.473      180026.587     1734013.545       179746.01
     1734001.292      179615.524     1733780.869      179452.438
     1733547.958      178378.044     1733458.952      178090.387
     1733335.994      177885.503     1733122.804      177700.494
     1732983.065      177484.944     1732764.141      177348.168
     1732460.569      177319.448     1732194.578      177181.003
      1732085.47       176996.82     1731881.057      176976.426
     1731333.484      176586.452     1731101.793      176331.303
     1730861.648      176152.419     1730748.315      175863.266
     1730585.657      175742.704     1730399.408      175407.506
     1729990.512      174883.084     1729867.989      174603.733
     1729820.817       174375.84     1729614.367      173969.677
     1729618.655      173809.173      1729578.94      173731.138

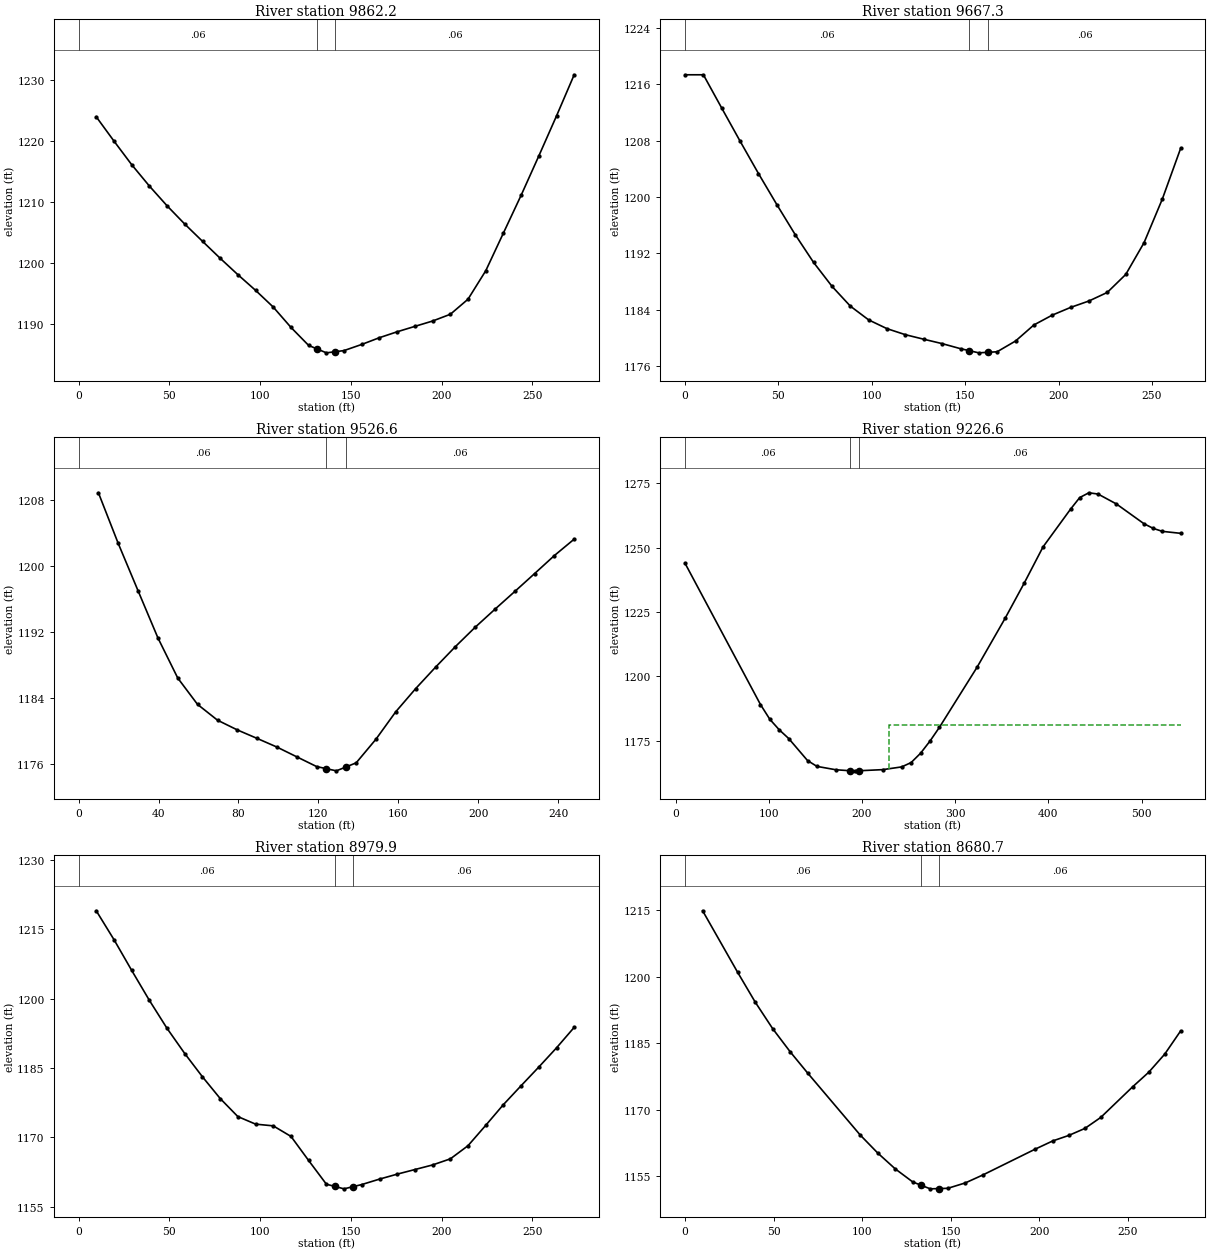
Type RM Length L Ch R = 1 ,9862.2  ,195.4,195,194.5
XS GIS Cut Line= 3
     1735186.503      180898.678     1735128.896      181022.426
     1735071.289      181146.175
#Sta/Elev= 30
     9.7 1223.92    19.5 1219.93    29.2 1216.09      39 1212.57    48.7 1209.35
    58.5 1206.34    68.3 1203.51      78 1200.74    87.7 1198.07    97.5 1195.49
   107.2 1192.76     117 1189.42   126.7 1186.48   131.5 1185.88   136.5 1185.26
   141.5 1185.45   146.2 1185.63     156 1186.64   165.7 1187.74   175.5 1188.71
   185.3  1189.6     195 1190.47   204.8 1191.58   214.5 1194.04   224.3 1198.71
     234 1204.87   243.8 1211.08   253.5 1217.49   263.3 1224.08     273  1230.8
#Mann= 3 , 0 , 0
       0     .06       0   131.5    .045       0   141.5     .06       0
Bank Sta=131.5,141.5
XS Rating Curve= 0 ,0
Exp/Cntr=0.3,0.1

Type RM Length L Ch R = 1 ,9667.3  ,141.1,140.7,140.2
XS GIS Cut Line= 2
     1735007.996      180826.508     1734901.124      181069.491
#Sta/Elev= 30
       0 1217.32     9.8 1217.32    19.7 1212.56    29.5 1207.89    39.3 1203.32
    49.2 1198.89      59 1194.65    68.8 1190.73    78.7 1187.33    88.5 1184.53
    98.3 1182.58   108.1 1181.34     118 1180.48   127.8 1179.84   137.6 1179.22
   147.5  1178.5   152.3 1178.21   157.3 1177.91   162.3 1177.99   167.1 1178.06
     177 1179.59   186.8 1181.86   196.6 1183.25   206.5 1184.35   216.3 1185.26
   226.1 1186.47     236 1189.02   245.8 1193.52   255.6 1199.71   265.4 1206.89
#Mann= 3 , 0 , 0
       0     .06       0   152.3    .045       0   162.3     .06       0
Bank Sta=152.3,162.3
XS Rating Curve= 0 ,0
Exp/Cntr=0.3,0.1

Type RM Length L Ch R = 1 ,9526.6  ,286.5,300,313.5
XS GIS Cut Line= 2
     1734874.285      180779.202     1734778.719      181008.088
#Sta/Elev= 27
     9.9 1208.89    19.8 1202.75    29.8 1196.96    39.7 1191.26    49.6  1186.4
    59.5  1183.2    69.5 1181.28    79.4  1180.1    89.3 1179.07    99.2 1178.02
   109.1 1176.84   119.1 1175.65     124 1175.39     129 1175.13     134 1175.62
   138.9  1176.1   148.8 1178.97   158.7  1182.3   168.7 1185.12   178.6 1187.71
   188.5  1190.2   198.4 1192.55   208.4 1194.76   218.3 1196.91   228.2 1199.08
   238.1 1201.27     248 1203.26
#Mann= 3 , 0 , 0
       0     .06       0     124    .045       0     134     .06       0
Bank Sta=124,134
XS Rating Curve= 0 ,0
Exp/Cntr=0.3,0.1

Type RM Length L Ch R = 1 ,9226.6  ,246.5,246.6,246.9
XS GIS Cut Line= 3
     1734755.829      180612.855     1734412.479      180806.657
     1734371.277      180948.575
#Sta/Elev= 30
    10.1 1243.89      91 1189.11   101.1 1183.35   111.2 1179.28   121.3 1175.92
   141.5 1167.37   151.6  1165.1   171.9 1163.79   187.1 1163.41   192.1 1163.37
   197.1 1163.41   222.4 1163.84   242.6  1164.9   252.7 1166.58   262.8 1170.18
     273 1174.94   283.1 1180.27   323.5 1203.59   353.8 1222.71   374.1 1236.24
   394.3 1250.29   423.8 1264.93   433.7 1269.45   443.5  1271.3   453.4  1270.8
   473.1 1266.95   502.6  1259.3   512.5 1257.49   522.3 1256.33     542 1255.56
#Mann= 3 , 0 , 0
    10.1     .06       0   187.1    .045       0   197.1     .06       0
#XS Ineff= 2 , 0
                          228.52         1181.25
Permanent Ineff=
       F       F
Bank Sta=187.1,197.1
XS Rating Curve= 0 ,0
Exp/Cntr=0.3,0.1

Type RM Length L Ch R = 1 ,8979.9  ,298.2,299.3,300.2
XS GIS Cut Line= 3
     1734630.945      180402.572      1734512.28      180470.023
     1734392.393      180535.342
#Sta/Elev= 30
     9.7 1219.03    19.5 1212.77    29.2 1206.15      39 1199.63    48.7 1193.59
    58.5 1188.12    68.2 1183.11      78  1178.4    87.7  1174.5    97.5 1172.86
   107.2 1172.49     117  1170.2   126.7    1165   136.5 1159.86   141.2 1159.38
   146.2 1158.86   151.2 1159.33     156 1159.79   165.8 1160.97   175.5 1162.04
   185.3 1163.04     195 1164.03   204.8 1165.35   214.5 1168.19   224.3 1172.61
     234 1177.08   243.8 1181.19   253.5 1185.21   263.3 1189.38     273  1193.8
#Mann= 3 , 0 , 0
       0     .06       0   141.2    .045       0   151.2     .06       0
Bank Sta=141.2,151.2
XS Rating Curve= 0 ,0
Exp/Cntr=0.3,0.1

Type RM Length L Ch R = 1 ,8680.7  ,422.4,417.8,413
XS GIS Cut Line= 3
     1734523.864      180139.188     1734337.706      180231.355
     1734265.607      180227.688
#Sta/Elev= 25
     9.9 1214.85    29.7 1200.96    39.6 1194.26    49.5 1188.25    59.4 1183.03
    69.2 1178.27    98.9 1164.29   108.8 1160.23   118.7 1156.65   128.6  1153.7
   133.5 1152.93   138.5 1152.15   143.5 1152.21   148.4 1152.27   158.3 1153.49
   168.2 1155.28   197.8 1161.11   207.7 1162.96   216.7 1164.19   225.8 1165.77
   234.8 1168.26   252.8 1175.16   261.9 1178.45   270.9 1182.52   279.9 1187.76
#Mann= 3 , 0 , 0
       0     .06       0   133.5    .045       0   143.5     .06       0
Bank Sta=133.5,143.5
XS Rating Curve= 0 ,0
Exp/Cntr=0.3,0.1

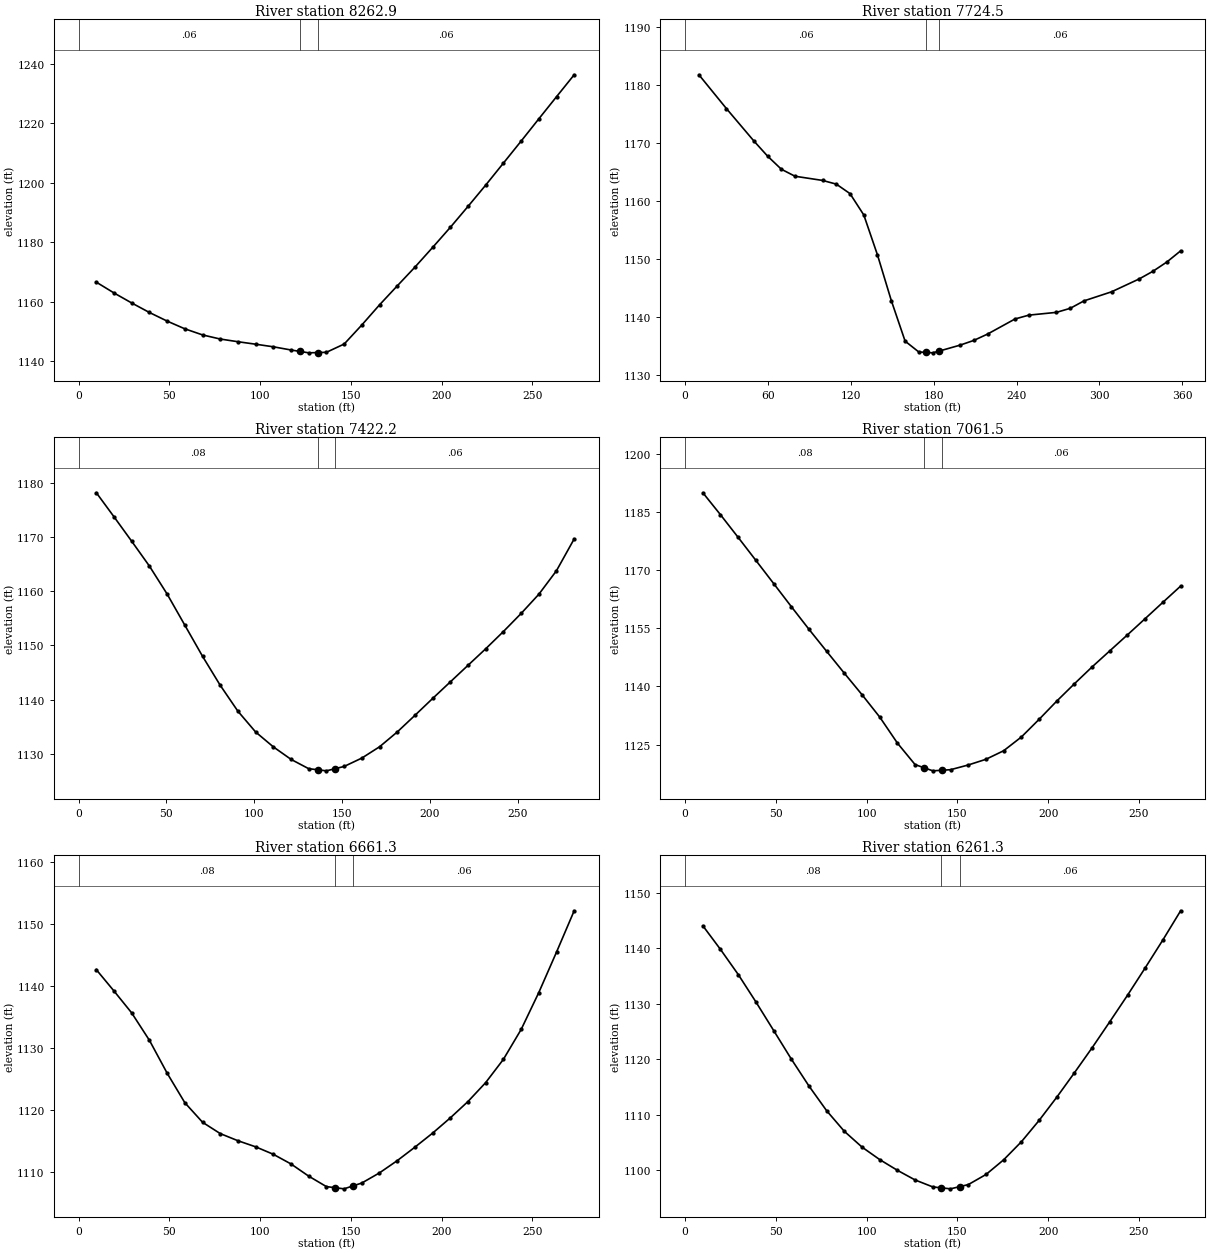
Type RM Length L Ch R = 1 ,8262.9  ,538.7,538.4,537.7
XS GIS Cut Line= 3
     1734242.954      179815.597     1734137.299      179902.031
     1734032.305      179989.256
#Sta/Elev= 30
     9.8 1166.54    19.5 1162.92    29.3 1159.53      39 1156.35    48.8 1153.44
    58.5 1150.85    68.3 1148.79      78 1147.41    87.8  1146.5    97.5 1145.67
   107.3 1144.79     117 1143.72   121.8 1143.25   126.8 1142.76   131.8 1142.86
   136.5 1142.94   146.3 1145.73     156 1152.13   165.8 1158.94   175.5 1165.29
   185.3 1171.64     195 1178.24   204.8 1185.04   214.5 1192.06   224.3 1199.28
     234 1206.64   243.8 1214.08   253.5 1221.54   263.3 1229.03     273  1236.4
#Mann= 3 , 0 , 0
       0     .06       0   121.8    .045       0   131.8     .06       0
Bank Sta=121.8,131.8
XS Rating Curve= 0 ,0
Exp/Cntr=0.3,0.1

Type RM Length L Ch R = 1 ,7724.5  ,290.6,302.3,315.3
XS GIS Cut Line= 3
     1733965.362      179384.426      1733786.82       179543.13
       1733756.3      179659.106
#Sta/Elev= 30
      10 1181.81    29.9 1175.98    49.8 1170.38    59.7 1167.77    69.7  1165.5
    79.6 1164.29    99.5 1163.57   109.5 1162.93   119.4 1161.29   129.4  1157.6
   139.3  1150.7   149.3 1142.83   159.3 1135.82   169.2 1133.95   174.2 1133.88
   179.2  1133.8   184.2 1134.12   199.1 1135.13     209 1135.94     219 1137.04
   238.9 1139.65   248.9 1140.31   268.9 1140.79   278.9 1141.49   288.8 1142.77
   308.8 1144.34   328.8 1146.56   338.8 1147.89   348.8 1149.48   358.8 1151.41
#Mann= 3 , 0 , 0
       0     .06       0   174.2    .045       0   184.2     .06       0
Bank Sta=174.2,184.2
XS Rating Curve= 0 ,0
Exp/Cntr=0.3,0.1

Type RM Length L Ch R = 1 ,7422.2  ,364.8,360.7,356.6
XS GIS Cut Line= 2
     1733868.792      179215.552     1733588.356      179247.276
#Sta/Elev= 30
    10.1 1178.18    20.2 1173.72    30.2 1169.24    40.3 1164.65    50.4 1159.48
    60.5 1153.72    70.6 1147.97    80.6 1142.65    90.7 1137.85   100.8 1134.01
   110.9 1131.26     121 1128.95     131 1127.24   136.1 1127.04   141.1 1126.84
   146.1 1127.24   151.2 1127.65   161.3  1129.2   171.4 1131.29   181.4    1134
   191.5 1137.08   201.6  1140.2   211.7 1143.27   221.7 1146.31   231.8 1149.37
   241.9 1152.56     252  1155.9   262.1 1159.45   272.1 1163.78   282.2 1169.66
#Mann= 3 , 0 , 0
       0     .08       0   136.1    .045       0   146.1     .06       0
Bank Sta=136.1,146.1
XS Rating Curve= 0 ,0
Exp/Cntr=0.3,0.1

Type RM Length L Ch R = 1 ,7061.5  ,397.8,400.2,402.6
XS GIS Cut Line= 3
     1733804.816      178840.863     1733675.911      178885.761
     1733547.007       178930.66
#Sta/Elev= 30
     9.8 1189.89    19.5 1184.23    29.2 1178.41      39 1172.46    48.8 1166.49
    58.5 1160.56    68.2 1154.73      78 1149.01    87.7  1143.4    97.5 1137.83
   107.3 1132.03     117 1125.35   126.7 1119.83   131.5 1119.04   136.5 1118.22
   141.5 1118.37   146.3 1118.52     156 1119.73   165.7 1121.19   175.5  1123.4
   185.3 1126.96     195 1131.48   204.7 1136.17   214.5 1140.67   224.2    1145
     234 1149.16   243.7 1153.27   253.5 1157.47   263.2 1161.65     273 1165.84
#Mann= 3 , 0 , 0
       0     .08       0   131.5    .045       0   141.5     .06       0
Bank Sta=131.5,141.5
XS Rating Curve= 0 ,0
Exp/Cntr=0.3,0.1

Type RM Length L Ch R = 1 ,6661.3  ,401.6,400,398.5
XS GIS Cut Line= 3
      1733705.53       178470.46     1733572.218      178499.788
     1733438.906      178529.117
#Sta/Elev= 30
     9.7 1142.65    19.5 1139.18    29.2 1135.66      39 1131.22    48.8 1125.89
    58.5 1121.14    68.3 1117.97      78 1116.15    87.7    1115    97.5 1114.01
   107.2 1112.81     117 1111.24   126.7 1109.28   136.5 1107.58   141.2 1107.41
   146.2 1107.22   151.2  1107.7     156 1108.16   165.7 1109.79   175.5 1111.77
   185.2 1113.94     195 1116.22   204.7 1118.67   214.5 1121.33   224.2 1124.37
     234 1128.14   243.8 1132.98   253.5 1138.93   263.3 1145.49     273 1152.15
#Mann= 3 , 0 , 0
       0     .08       0   141.2    .045       0   151.2     .06       0
Bank Sta=141.2,151.2
XS Rating Curve= 0 ,0
Exp/Cntr=0.3,0.1

Type RM Length L Ch R = 1 ,6261.3  ,359.2,349.4,339.5
XS GIS Cut Line= 3
     1733596.956      178074.957     1733466.397      178114.789
     1733335.742      178154.305
#Sta/Elev= 30
     9.8 1144.05    19.5  1139.8    29.3 1135.27      39 1130.35    48.8 1125.19
    58.5 1120.06    68.3 1115.17      78 1110.74    87.7 1107.05    97.5 1104.19
   107.2 1101.95     117 1100.01   126.7 1098.28   136.5 1097.02   141.2 1096.86
   146.2 1096.68   151.2 1097.07     156 1097.44   165.8 1099.27   175.5 1101.91
   185.3 1105.17     195 1108.99   204.8  1113.2   214.5 1117.59   224.3 1122.12
     234 1126.79   243.8 1131.58   253.5 1136.49   263.3 1141.55     273 1146.76
#Mann= 3 , 0 , 0
       0     .08       0   141.2    .045       0   151.2     .06       0
Bank Sta=141.2,151.2
XS Rating Curve= 0 ,0
Exp/Cntr=0.3,0.1

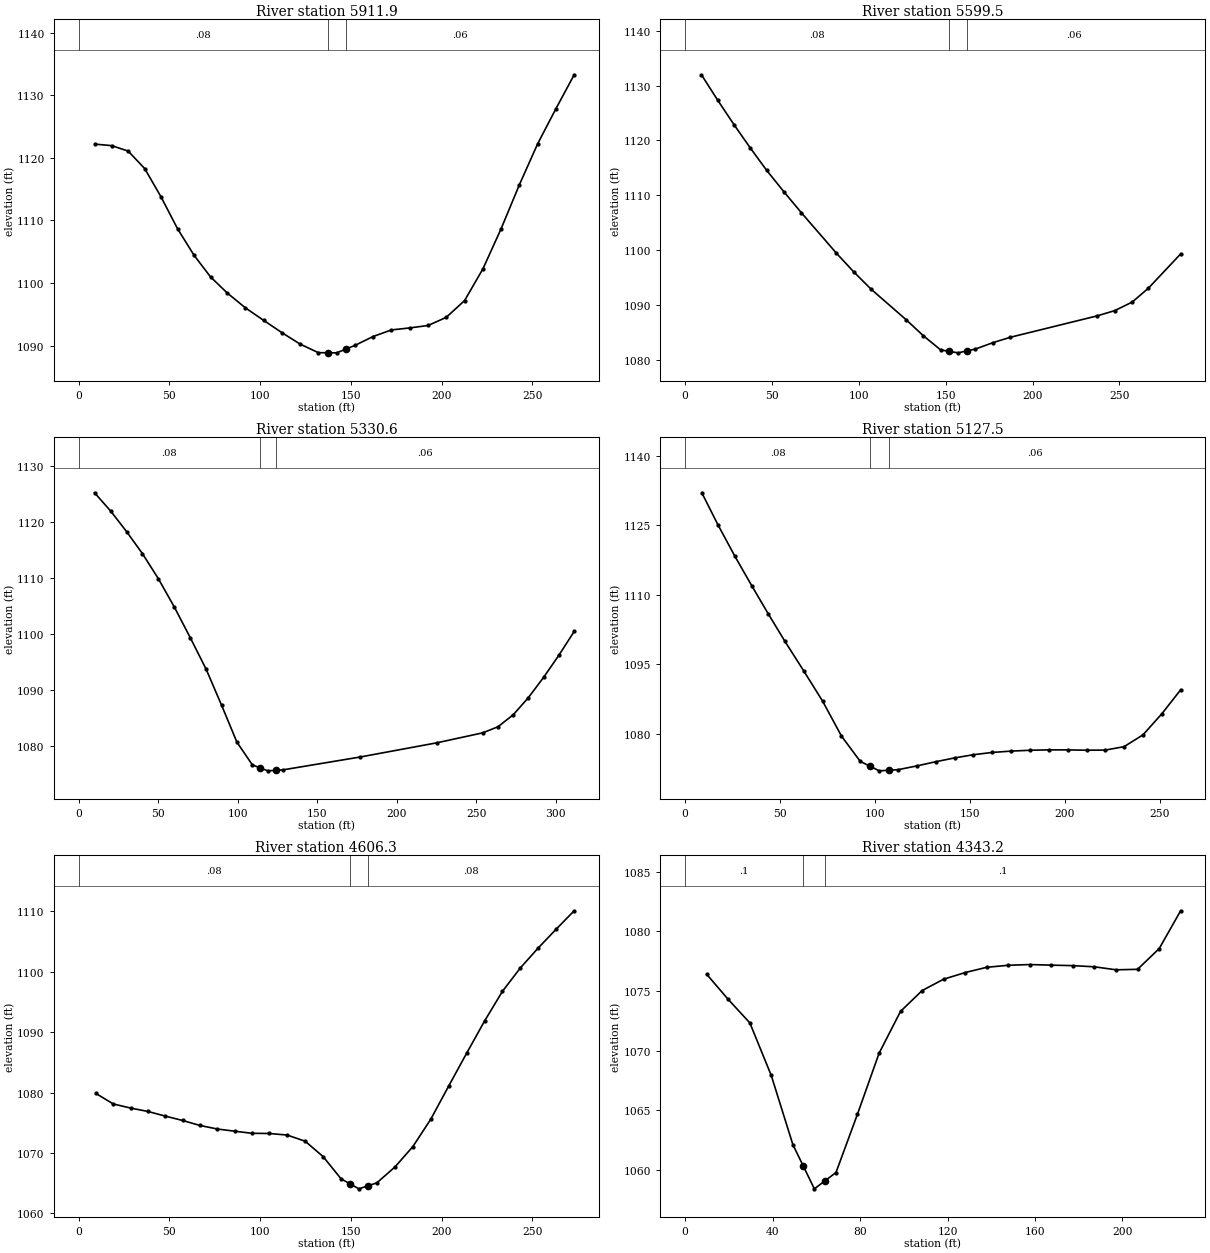
Type RM Length L Ch R = 1 ,5911.9  ,311.5,312.4,313.4
XS GIS Cut Line= 3
     1733374.972      177734.959     1733314.514      177790.042
     1733179.312      177925.412
#Sta/Elev= 30
     9.1 1122.19    18.2 1121.95    27.3 1121.08    36.4 1118.29    45.4 1113.77
    54.5 1108.68    63.6 1104.44    72.7 1100.98    81.8 1098.44    91.9 1096.04
   101.9 1094.05     112 1092.08   122.1 1090.24   132.1 1088.88   137.2 1088.86
   142.2 1088.85   147.2 1089.44   152.3 1090.04   162.3 1091.46   172.4 1092.51
   182.5 1092.83   192.6 1093.22   202.6 1094.52   212.7  1097.2   222.8 1102.26
   232.8 1108.65   242.9  1115.7     253 1122.26     263 1127.83   273.1 1133.27
#Mann= 3 , 0 , 0
       0     .08       0   137.2    .045       0   147.2     .06       0
Bank Sta=137.2,147.2
XS Rating Curve= 0 ,0
Exp/Cntr=0.3,0.1

Type RM Length L Ch R = 1 ,5599.5  ,273.8,268.9,264
XS GIS Cut Line= 4
     1733197.113      177519.459     1733151.163       177528.92
     1732997.095      177672.175     1732979.526      177693.799
#Sta/Elev= 24
     9.4 1131.97    18.8 1127.32    28.1  1122.9    37.5 1118.64    46.9 1114.57
    56.9 1110.63    66.9 1106.83      87 1099.48      97 1096.06     107  1092.9
   127.1 1087.35   137.1  1084.4   147.1 1081.81   152.1 1081.55   157.1 1081.28
   162.1 1081.63   167.1 1081.97   177.1 1083.13   187.2 1084.12   237.3 1088.03
   247.3 1088.98   257.3 1090.53   266.6 1093.05   285.2 1099.31
#Mann= 3 , 0 , 0
       0     .08       0   152.1    .045       0   162.1     .06       0
Bank Sta=152.1,162.1
XS Rating Curve= 0 ,0
Exp/Cntr=0.3,0.1

Type RM Length L Ch R = 1 ,5330.6  ,211.1,203.1,195.1
XS GIS Cut Line= 4
     1732966.327      177338.136     1732902.757      177387.036
     1732823.635       177508.63     1732803.326      177592.418
#Sta/Elev= 24
      10 1125.18    20.1 1121.94    30.1 1118.28    40.1 1114.34    50.1 1109.88
    60.2  1104.8    70.2 1099.35    80.2 1093.72    89.9  1087.3    99.5 1080.75
   109.2  1076.7   113.9 1076.19   118.9 1075.64   123.9 1075.73   128.6 1075.82
   176.9  1078.1   225.3 1080.64     254 1082.41   263.6 1083.49   273.2 1085.63
   282.7 1088.68   292.3  1092.3   301.9 1096.24   311.5 1100.47
#Mann= 3 , 0 , 0
       0     .08       0   113.9    .045       0   123.9     .06       0
Bank Sta=113.9,123.9
XS Rating Curve= 0 ,0
Exp/Cntr=0.3,0.1

Type RM Length L Ch R = 1 ,5127.5  ,515.4,521.1,526.9
XS GIS Cut Line= 3
     1732728.105      177237.058     1732709.086      177286.107
      1732672.05      177491.309
#Sta/Elev= 29
     8.8 1131.97    17.5 1124.91    26.3 1118.22    35.1 1111.92    43.8 1105.85
    52.6  1099.9    62.5 1093.53    72.5 1086.96    82.4 1079.45    92.3 1073.99
    97.3 1072.97   102.3 1071.95   107.3 1072.07   112.2  1072.2   122.1 1073.01
     132 1073.91     142 1074.74   151.9 1075.43   161.8 1075.92   171.8 1076.21
   181.7 1076.39   191.6 1076.48   201.5 1076.47   211.5  1076.4   221.4 1076.43
   231.3 1077.17   241.3 1079.73   251.2 1084.27   261.1 1089.43
#Mann= 3 , 0 , 0
       0     .08       0    97.3    .045       0   107.3     .06       0
Bank Sta=97.3,107.3
XS Rating Curve= 0 ,0
Exp/Cntr=0.3,0.1

Type RM Length L Ch R = 1 ,4606.3  ,261.3,263.2,265
XS GIS Cut Line= 3
     1732278.852      177053.718     1732234.617      177148.971
     1732159.425      177299.209
#Sta/Elev= 30
     9.5 1079.87    19.1 1078.12    28.6 1077.45    38.2 1076.88    47.7 1076.12
    57.3 1075.39    66.8 1074.57    76.4 1073.98    85.9 1073.62    95.5 1073.27
     105 1073.24   114.9 1072.98   124.8 1071.96   134.7 1069.41   144.6 1065.73
   149.4 1064.93   154.4 1064.08   159.4 1064.58   164.3 1065.07   174.2 1067.68
   184.1 1071.06     194  1075.6   203.8 1081.05   213.7 1086.49   223.6 1091.83
   233.5 1096.77   243.4 1100.65   253.3 1103.97   263.1 1107.05     273 1110.09
#Mann= 3 , 0 , 0
       0     .08       0   149.4    .045       0   159.4     .08       0
Bank Sta=149.4,159.4
XS Rating Curve= 0 ,0
Exp/Cntr=0.3,0.1

Type RM Length L Ch R = 1 ,4343.2  ,462.1,464.8,467.5
XS GIS Cut Line= 2
      1732095.48      176931.756     1731980.366      177126.949
#Sta/Elev= 25
     9.9  1076.4    19.7  1074.3    29.6 1072.33    39.4 1067.92    49.3 1062.11
    54.1  1060.3    59.1 1058.41    64.1  1059.1      69 1059.78    78.8 1064.66
    88.7 1069.78    98.5 1073.29   108.4 1075.04   118.2 1075.99   128.1 1076.55
   137.9 1076.99   147.8 1077.16   157.6 1077.22   167.5 1077.17   177.3 1077.13
   187.2 1077.03   197.1 1076.78   206.9 1076.82   216.8 1078.56   226.6 1081.73
#Mann= 3 , 0 , 0
       0      .1       0    54.1    .045       0    64.1      .1       0
Bank Sta=54.1,64.1
XS Rating Curve= 0 ,0
Exp/Cntr=0.3,0.1

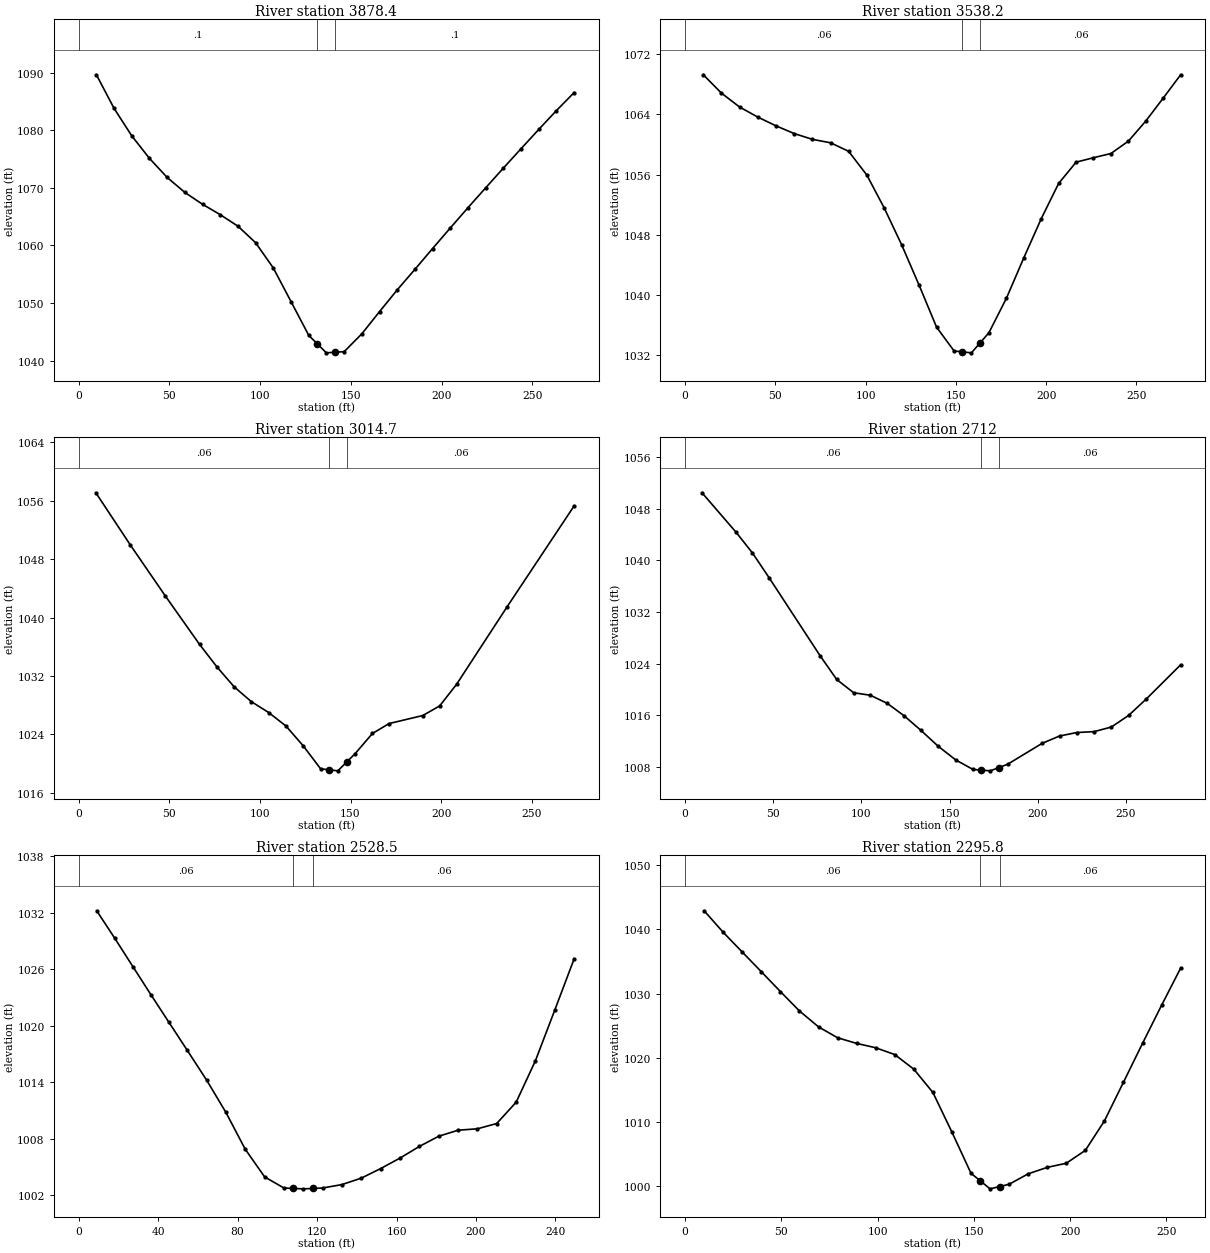
Type RM Length L Ch R = 1 ,3878.4  ,342,340.2,338.4
XS GIS Cut Line= 3
     1731751.514      176696.968     1731665.209      176802.721
     1731578.905      176908.474
#Sta/Elev= 30
     9.8 1089.61    19.5 1083.79    29.3    1079      39 1075.11    48.7 1071.82
    58.5  1069.2    68.3 1067.13      78 1065.34    87.8 1063.33    97.5 1060.47
   107.2 1056.11     117 1050.26   126.8 1044.38   131.5 1042.92   136.5 1041.36
   141.5 1041.47   146.3 1041.57     156 1044.65   165.8 1048.52   175.5 1052.28
   185.3 1055.86     195 1059.46   204.8 1063.04   214.5 1066.55   224.3 1070.01
     234 1073.42   243.7 1076.77   253.5 1080.13   263.2 1083.39     273 1086.53
#Mann= 3 , 0 , 0
       0      .1       0   131.5    .045       0   141.5      .1       0
Bank Sta=131.5,141.5
XS Rating Curve= 0 ,0
Exp/Cntr=0.3,0.1

Type RM Length L Ch R = 1 ,3538.2  ,524,523.5,523.8
XS GIS Cut Line= 3
     1731450.173      176481.758     1731411.397      176574.684
      1731313.68      176718.472
#Sta/Elev= 30
    10.1 1069.25    20.1 1066.82    30.2 1064.97    40.3 1063.63    50.3 1062.48
    60.4 1061.45    70.5 1060.68    80.6 1060.22    90.6 1059.09   100.7 1055.93
   110.4 1051.52     120 1046.66   129.7 1041.28   139.3 1035.75     149 1032.59
   153.6 1032.47   158.6 1032.34   163.6 1033.71   168.3 1035.01     178 1039.59
   187.6 1044.94   197.3 1050.15   206.9 1054.82   216.6 1057.65   226.2 1058.24
   235.9  1058.8   245.6 1060.45   255.2 1063.11   264.9 1066.17   274.5 1069.25
#Mann= 3 , 0 , 0
       0     .06       0   153.6    .045       0   163.6     .06       0
Bank Sta=153.6,163.6
XS Rating Curve= 0 ,0
Exp/Cntr=0.3,0.1

Type RM Length L Ch R = 1 ,3014.7  ,293.1,302.7,312.2
XS GIS Cut Line= 3
     1731082.169      176149.492     1730993.797      176285.336
     1730923.143      176371.392
#Sta/Elev= 22
     9.5 1057.09    28.6 1049.91    47.7    1043    66.7 1036.32    76.3 1033.23
    85.8  1030.5    95.3 1028.47   104.9 1026.97   114.4 1025.13   123.9 1022.42
   133.5 1019.27     138 1019.14     143 1018.99     148 1020.22   152.5 1021.33
   162.1 1024.11   171.3 1025.47   189.9 1026.57   199.2 1027.89   208.5 1030.84
   236.3 1041.43   273.4  1055.3
#Mann= 3 , 0 , 0
       0     .06       0     138    .045       0     148     .06       0
Bank Sta=138,148
XS Rating Curve= 0 ,0
Exp/Cntr=0.3,0.1

Type RM Length L Ch R = 1 ,2712    ,183.2,183.4,183.7
XS GIS Cut Line= 3
      1730963.06      175987.519     1730837.392      176033.524
     1730710.704      176108.599
#Sta/Elev= 26
     9.6 1050.46    28.7 1044.42    38.2 1041.15    47.8 1037.25    76.5 1025.27
      86 1021.56    95.6 1019.51   105.1 1019.12   114.7 1017.86   124.3 1015.93
   133.8 1013.68   143.6 1011.22   153.5 1009.11   163.3 1007.64   168.1 1007.53
   173.1 1007.42   178.1 1007.93   182.9 1008.43   202.5 1011.67   212.4 1012.81
   222.2 1013.35     232 1013.49   241.8  1014.2   251.6    1016   261.5 1018.51
   281.1 1023.83
#Mann= 3 , 0 , 0
       0     .06       0   168.1    .045       0   178.1     .06       0
Bank Sta=168.1,178.1
XS Rating Curve= 0 ,0
Exp/Cntr=0.3,0.1

Type RM Length L Ch R = 1 ,2528.5  ,231.4,232.8,234.1
XS GIS Cut Line= 3
     1730838.956      175834.891     1730788.907      175856.787
      1730619.99      175953.758
#Sta/Elev= 28
     9.1 1032.19    18.2 1029.27    27.3 1026.27    36.4 1023.28    45.5 1020.34
    54.6 1017.41    64.4 1014.23    74.1 1010.81    83.8 1006.91    93.6 1003.96
   103.3 1002.78   108.1 1002.73   113.1 1002.69   118.1 1002.73   122.8 1002.78
   132.5 1003.14   142.3 1003.83     152 1004.84   161.8 1005.96   171.5 1007.19
   181.2 1008.27     191 1008.91   200.7 1009.06   210.4 1009.62   220.2 1011.88
   229.9 1016.28   239.7 1021.69   249.4  1027.1
#Mann= 3 , 0 , 0
       0     .06       0   108.1    .045       0   118.1     .06       0
Bank Sta=108.1,118.1
XS Rating Curve= 0 ,0
Exp/Cntr=0.3,0.1

Type RM Length L Ch R = 1 ,2295.8  ,483.8,481.2,478.6
XS GIS Cut Line= 2
     1730725.426      175661.331     1730492.796      175771.423
#Sta/Elev= 28
     9.9 1042.91    19.8 1039.55    29.7 1036.47    39.6  1033.4    49.5 1030.31
    59.4 1027.28    69.3  1024.8    79.2  1023.1    89.1 1022.22      99 1021.54
   108.9 1020.48   118.8  1018.2   128.7 1014.57   138.6 1008.38   148.5 1001.96
   153.4 1000.76   158.4  999.53   163.4  999.89   168.3 1000.24   178.2 1001.87
   188.1 1002.88     198 1003.52   207.9 1005.53   217.8 1010.12   227.7 1016.16
   237.6 1022.22   247.5 1028.17   257.4 1033.96
#Mann= 3 , 0 , 0
       0     .06       0   153.4    .045       0   163.4     .06       0
Bank Sta=153.4,163.4
XS Rating Curve= 0 ,0
Exp/Cntr=0.3,0.1

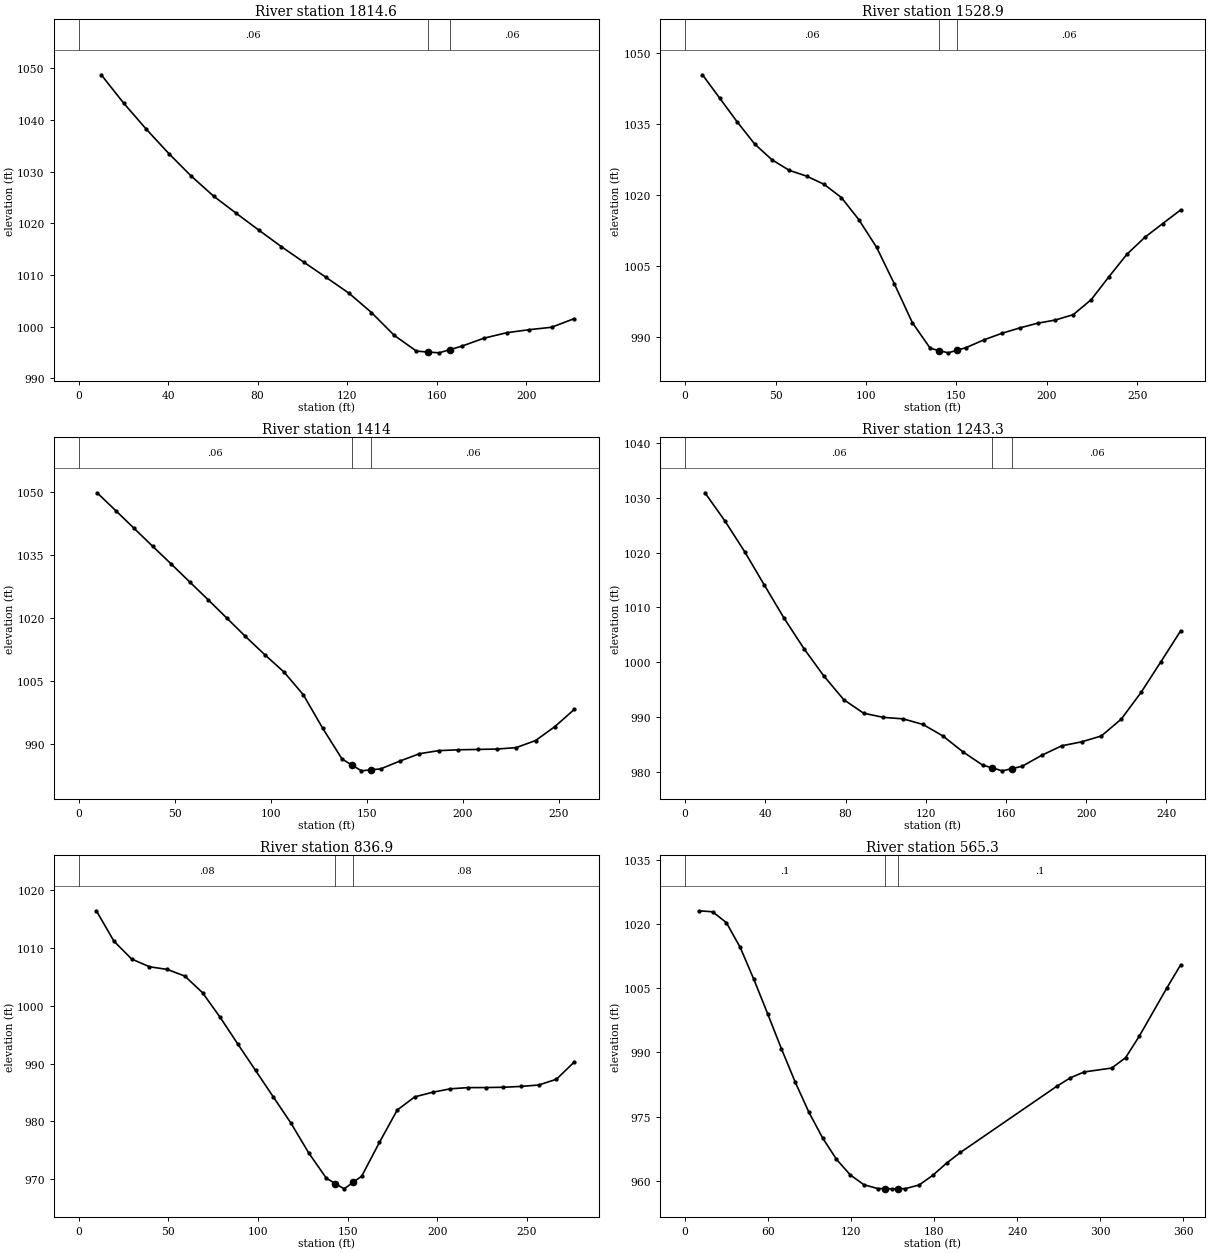
Type RM Length L Ch R = 1 ,1814.6  ,286.4,285.7,285
XS GIS Cut Line= 2
     1730458.901      175239.001     1730272.611      175358.816
#Sta/Elev= 24
    10.1 1048.77    20.1  1043.3    30.2 1038.26    40.3 1033.53    50.3 1029.18
    60.4 1025.26    70.5 1021.95    80.5 1018.72    90.6 1015.52   100.7 1012.49
   110.7 1009.54   120.8 1006.51   130.9 1002.76     141  998.37     151  995.29
   156.1  995.12   161.1  994.96   166.1   995.6   171.2  996.24   181.2   997.8
   191.3  998.85   201.4  999.44   211.4  999.91   221.5 1001.58
#Mann= 3 , 0 , 0
       0     .06       0   156.1    .045       0   166.1     .06       0
Bank Sta=156.1,166.1
XS Rating Curve= 0 ,0
Exp/Cntr=0.3,0.1

Type RM Length L Ch R = 1 ,1528.9  ,110.9,114.9,118.9
XS GIS Cut Line= 3
     1730275.772      175003.529     1730203.618      175066.783
     1730057.703      175168.592
#Sta/Elev= 30
     9.6 1045.32    19.2 1040.35    28.8 1035.38    38.4 1030.73      48 1027.38
    57.6 1025.15    67.2 1023.92    76.8 1022.21    86.4  1019.4      96 1014.76
   105.8 1008.93   115.7 1001.16   125.6  993.01   135.5  987.58   140.4  987.11
   145.4  986.63   150.4  987.19   155.3  987.73   165.1  989.36     175  990.74
   184.9  991.88   194.8  992.88   204.7  993.56   214.6   994.7   224.5  997.87
   234.3 1002.71   244.2 1007.43   254.1 1011.01     264 1013.92   273.9 1016.79
#Mann= 3 , 0 , 0
       0     .06       0   140.4    .045       0   150.4     .06       0
Bank Sta=140.4,150.4
XS Rating Curve= 0 ,0
Exp/Cntr=0.3,0.1

Type RM Length L Ch R = 1 ,1414    ,172.9,170.7,168.5
XS GIS Cut Line= 3
     1730241.597      174944.079     1730159.736      174972.745
     1730002.585      175040.695
#Sta/Elev= 28
     9.6 1049.72    19.3 1045.48    28.9 1041.24    38.5 1036.99    48.2 1032.75
    57.8 1028.49    67.5  1024.2    77.1 1019.89    86.7 1015.56    96.8 1011.19
   106.9 1007.02   116.9 1001.64     127  993.66   137.1  986.31   142.2  984.89
   147.2   983.5   152.2  983.74   157.2  983.97   167.3  985.85   177.4  987.58
   187.4  988.31   197.5  988.51   207.6   988.6   217.7  988.69   227.7  989.03
   237.8  990.71   247.9  994.05   257.9  998.11
#Mann= 3 , 0 , 0
       0     .06       0   142.2    .045       0   152.2     .06       0
Bank Sta=142.2,152.2
XS Rating Curve= 0 ,0
Exp/Cntr=0.3,0.1

Type RM Length L Ch R = 1 ,1243.3  ,403.8,406.4,408.9
XS GIS Cut Line= 2
     1730125.333      174800.725     1729909.934      174921.887
#Sta/Elev= 27
     9.9 1030.92    19.8 1025.81    29.7 1020.17    39.5 1014.08    49.4    1008
    59.3 1002.45    69.2  997.47    79.1  993.16      89  990.68    98.9  989.92
   108.7  989.65   118.6  988.63   128.5  986.54   138.4  983.67   148.3  981.22
   153.2  980.69   158.2  980.16   163.2  980.58   168.1     981   177.9  983.01
   187.8  984.73   197.7  985.45   207.6  986.53   217.5  989.61   227.4  994.49
   237.3  1000.1   247.1 1005.71
#Mann= 3 , 0 , 0
       0     .06       0   153.2    .045       0   163.2     .06       0
Bank Sta=153.2,163.2
XS Rating Curve= 0 ,0
Exp/Cntr=0.3,0.1

Type RM Length L Ch R = 1 ,836.9   ,270.3,271.7,273.1
XS GIS Cut Line= 2
     1729983.229       174444.72     1729727.444      174549.427
#Sta/Elev= 30
     9.9 1016.47    19.7  1011.2    29.6 1008.11    39.5 1006.77    49.4 1006.31
    59.2 1005.16    69.1 1002.28      79  997.98    88.8  993.37    98.7   988.8
   108.6  984.21   118.5  979.64   128.3  974.53   138.2  970.12   143.1  969.21
   148.1  968.29   153.1  969.41   157.9  970.49   167.8  976.35   177.7  981.94
   187.5  984.23   197.4  985.02   207.3  985.62   217.2  985.83     227  985.84
   236.9  985.89   246.8  986.04   256.6  986.28   266.5  987.28   276.4  990.25
#Mann= 3 , 0 , 0
       0     .08       0   143.1    .045       0   153.1     .08       0
Bank Sta=143.1,153.1
XS Rating Curve= 0 ,0
Exp/Cntr=0.3,0.1

Type RM Length L Ch R = 1 ,565.3   ,185.3,184.1,182.9
XS GIS Cut Line= 2
     1729898.655      174200.857     1729558.974      174314.084
#Sta/Elev= 30
     9.9  1023.1    19.9 1022.86    29.8 1020.34    39.8 1014.56    49.7 1007.07
    59.7  999.01    69.6  990.87    79.6  983.06    89.5  976.01    99.5  969.96
   109.4  965.04   119.4  961.38   129.3  959.09   139.2  958.21   144.2  958.18
   149.2  958.14   154.2  958.16   159.1  958.19   169.1  959.04     179   961.3
     189  964.16   198.9  966.63   268.5  982.08   278.5   984.1   288.4  985.45
   308.3  986.36   318.3  988.77   328.2   993.8   348.1 1005.05   358.1 1010.46
#Mann= 3 , 0 , 0
       0      .1       0   144.2    .045       0   154.2      .1       0
Bank Sta=144.2,154.2
XS Rating Curve= 0 ,0
Exp/Cntr=0.3,0.1

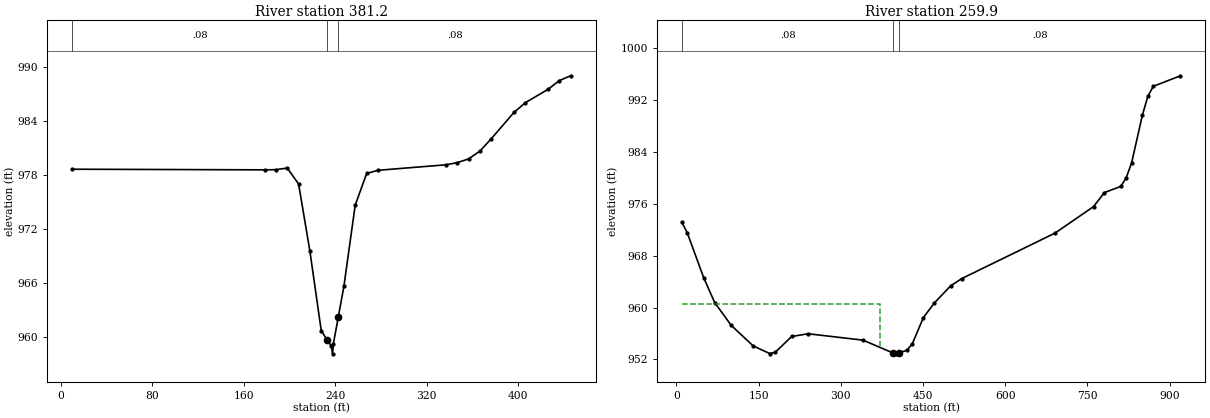
Type RM Length L Ch R = 1 ,381.2   ,118.8,121.3,123.7
XS GIS Cut Line= 2
     1729875.131      174007.689     1729460.883      174172.765
#Sta/Elev= 26
     9.9  978.61   178.4  978.54   188.3  978.56   198.2  978.74   208.1  976.97
     218   969.5   227.9  960.69   232.8  959.71  236.76  958.96   237.8  958.12
  238.45  959.19   242.8   962.2   247.7  965.61   257.6  974.62   267.6  978.14
   277.5  978.49   336.9   979.1   346.8  979.34   356.7  979.75   366.7  980.63
   376.6     982   396.4  984.91   406.3  985.99   426.1  987.47     436  988.44
   445.9  988.98
#Mann= 3 , 0 , 0
     9.9     .08       0   232.8    .045       0   242.8     .08       0
Bank Sta=232.8,242.8
XS Rating Curve= 0 ,0
Exp/Cntr=0.3,0.1

Type RM Length L Ch R = 1 ,259.9   ,265.8,259.9,254
XS GIS Cut Line= 3
     1730026.036      173871.791      1729290.06        174066.4
     1729190.986      174190.242
#Sta/Elev= 30
      10  973.14      20  971.49    50.1  964.55    70.1  960.75   100.2  957.25
   140.2  954.09   170.3  952.92   180.3  953.09   210.4  955.54   240.4  955.96
   340.6  954.98   395.7  952.99   400.7  952.87   405.7  953.03   420.7  953.41
   430.7  954.44   450.8  958.46   470.8   960.7   500.8  963.36   520.9  964.46
   691.2  971.47   761.3  975.54   781.1   977.7   810.8  978.64   820.7  979.94
   830.7  982.25   850.5  989.67   860.4  992.52   870.3  994.06   919.9  995.68
#Mann= 3 , 0 , 0
      10     .08       0   395.7    .045       0   405.7     .08       0
#XS Ineff= 2 , 0
          372.48  960.52
Permanent Ineff=
       F       F
Bank Sta=395.7,405.7
XS Rating Curve= 0 ,0
Exp/Cntr=0.3,0.1
Stream Node=Johnnycake Br...,Main            , 0 , 0 ,Upstream end
Stream Node=Johnnycake Br...,Main            , 0 , 1 ,Downstream end

Chan Stop Cuts=-1
Use User Specified Reach Order=0